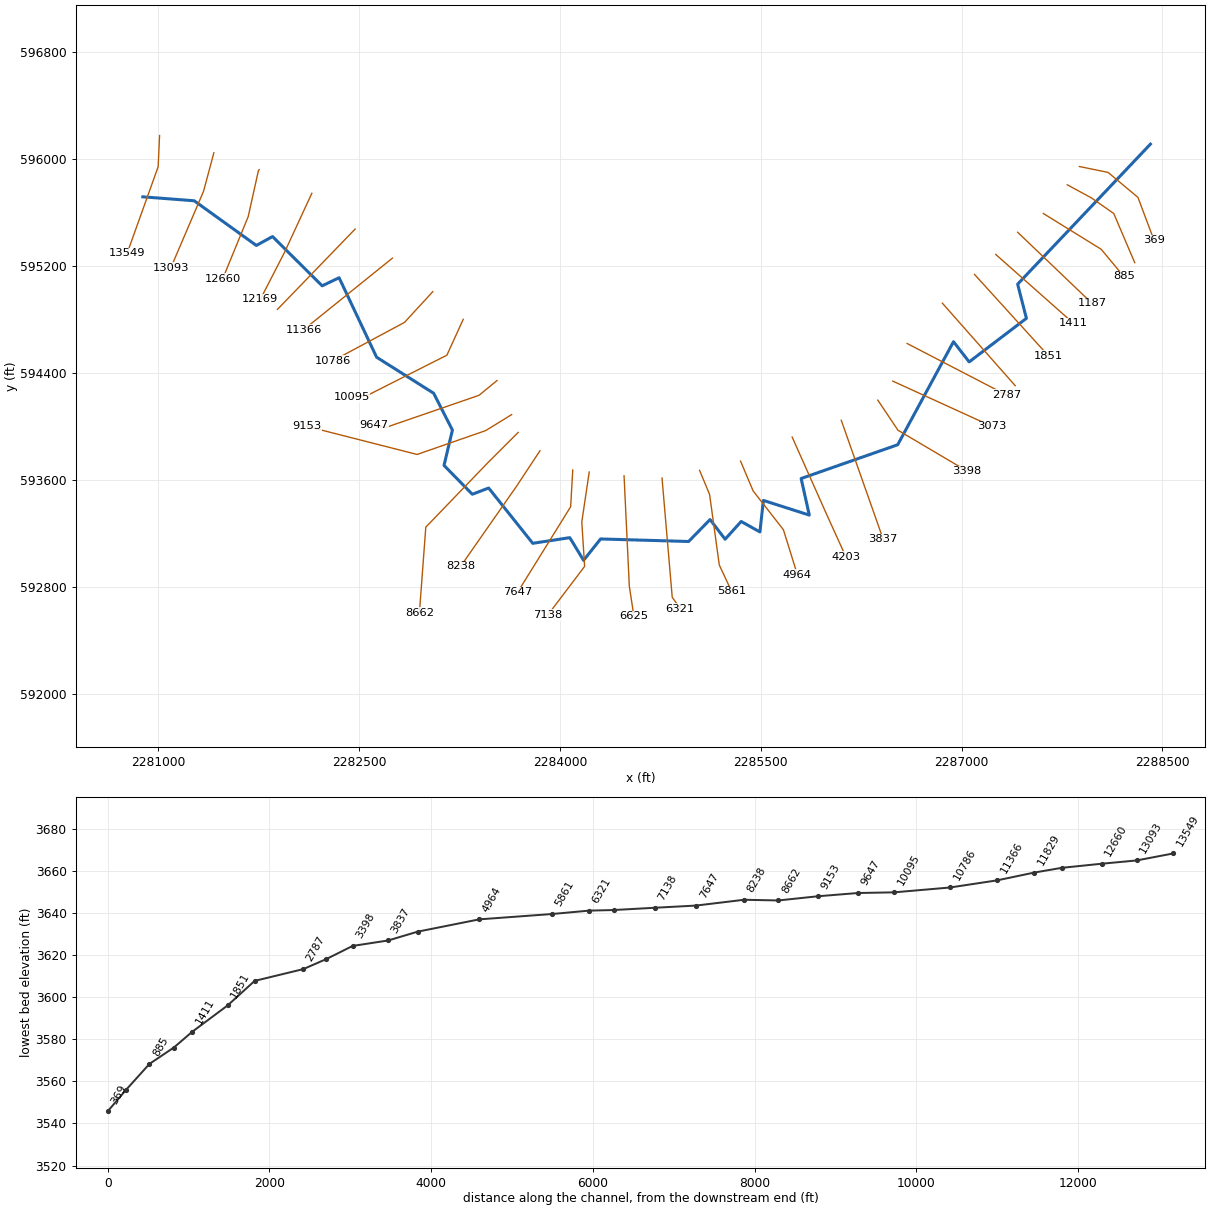
--- REDRN_2.prj (project) ---

Proj Title=REDRN_2
Current Plan=p01
Default Exp/Contr=0,0
English Units
Geom File=g01
Flow File=f01
Plan File=p01
BEGIN DESCRIPTION:
----------MODEL BY WOOD PLC 2022----------
AFH study
Randolph County, WV
HEC-RAS Version: RAS 6.2
Vertical Datum: NAVD88
Projection: NAD 1983 StatePlane West Virginia S FIPS 4702 (US Feet)
Terrain: 1-meter LIDAR (FEMA Region III 3DEP collected 2016-2018)
Land Use: 2019 NLCD
Hydrologic Method:
WV SIR2010-5033 regression equations
Additional Model Notes:
None
END DESCRIPTION:
DSS Export Rating Curves= 0
DSS Export Rating Curve Sorted= 0
DSS Export Volume Flow Curves= 0
DXF OffsetX= 0
DXF OffsetY= 0
DXF ScaleX= 0
DXF ScaleY= 0

--- REDRN_2.p01 (plan) ---

Plan Title=Floodplain
Program Version=6.20
Short Identifier=Floodplain
Geom File=g01
Flow File=f01
Subcritical Flow
K Sum by GR= 0
Std Step Tol= 0.01
Critical Tol= 0.01
Num of Std Step Trials= 20
Max Error Tol= 0.3
Flow Tol Ratio= 0.001
Split Flow NTrial= 30
Split Flow Tol= 0.02
Split Flow Ratio= 0.02
Log Output Level= 0
Friction Slope Method= 1
Unsteady Friction Slope Method= 2
Unsteady Bridges Friction Slope Method= 1
Parabolic Critical Depth
Global Vel Dist= 0 , 0 , 0
Global Log Level= 0
CheckData=True
Encroach Param=-1 ,0,0, 0
Mapping Interval=1HOUR
Computation Time Step Use Courant=        0
Computation Time Step Use Time Series=    0
Computation Time Step Count To Double=0
Computation Time Step Max Doubling=0
Computation Time Step Max Halving=0
Computation Time Step Residence Courant=0
Run HTab= 0
Run UNet= 0
Run Sediment= 0
Run PostProcess= 0
Run WQNet= 0
Run RASMapper=-1
UNET Theta= 0
UNET Theta Warmup= 0
UNET ZTol= 0
UNET ZSATol= 0
UNET MxIter= 0
UNET Max Iter WO Improvement= 0
UNET MaxInSteps= 0
UNET DtIC= 0
UNET DtMin= 0
UNET MaxCRTS= 0
UNET WFStab= 0
UNET SFStab= 0
UNET WFX= 1
UNET SFX= 1
UNET Gravity=32.174
UNET 1D Methodology=Finite Difference
UNET DSS MLevel= 1
UNET Pardiso=0
UNET DZMax Abort= 0
UNET Use Existing IB Tables= 0
UNET Froude Reduction=False
UNET Froude Limit= 0
UNET Froude Power= 0
UNET D1 Cores= 0
UNET WindReference=Eulerian
UNET WindDragFormulation=Hsu (1988)
UNET D2 Coriolis=0
UNET D2 Cores= 0
UNET D2 Theta= 1
UNET D2 Theta Warmup= 1
UNET D2 Z Tol= 0.01
UNET D2 Volume Tol= 0.01
UNET D2 Max Iterations= 20
UNET D2 Equation= 0
UNET D2 RampUpFraction=0.1
UNET D2 TimeSlices= 1
UNET D2 Turbulence Formulation=Non-Conservative (original)
UNET D2 Eddy Viscosity=0.3
UNET D2 Transverse Eddy Viscosity=0.1
UNET D2 Smagorinsky Mixing=0
UNET D2 BCVolumeCheck=0
UNET D2 Cores=0
UNET D2 SolverType=PARDISO (Direct)
UNET D2 Minimum Iterations= 2147483647
UNET D2 Maximum Iterations= 2147483647
UNET D2 Restart Number= 10
UNET D2 Relaxation Coeff=1.3
UNET D2 SOR Precondition Iterations= 10
UNET D2 ILUT Maximum Fill= 8
UNET D2 ILUT Tolerance=1E-08
UNET D1D2 MaxIter= 0
UNET D1D2 ZTol=0.01
UNET D1D2 QTol=0.1
UNET D1D2 MinQTol=1
Write IC File= 0
Write IC File at Fixed DateTime=0
Write IC File at Sim End=0
Echo Input=False
Echo Parameters=False
Echo Output=False
Write Detailed= 0
HDF Write Warmup=0
HDF Write Time Slices=0
HDF Flush=0
HDF Compression= 1
HDF Chunk Size= 1
HDF Spatial Parts= 1
HDF Use Max Rows=0
HDF Fixed Rows= 1
Calibration Method= 0
Calibration Iterations= 20
Calibration Max Change=0.05
Calibration Tolerance=0.2
Calibration Maximum=1.5
Calibration Minimum=0.5
Calibration Optimization Method= 1
WQ AD Non Conservative
WQ ULTIMATE=-1
WQ Max Comp Step=1HOUR
WQ Output Interval=15MIN
WQ Output Selected Increments= 0
WQ Output face flow=0
WQ Output face velocity=0
WQ Output face area=0
WQ Output face dispersion=0
WQ Output cell volume=0
WQ Output cell surface area=0
WQ Output cell continuity=0
WQ Output cumulative cell continuity=0
WQ Output face conc=0
WQ Output face dconc_dx=0
WQ Output face courant=0
WQ Output face peclet=0
WQ Output face adv mass=0
WQ Output face disp mass=0
WQ Output cell mass=0
WQ Output cell source sink temp=0
WQ Output nsm pathways=0
WQ Output nsm derived pathways=0
WQ Create Restart=0
WQ Fixed Restart=0
WQ System Summary=0
WQ Write To DSS=0
Sorting and Armoring Iterations= 10
XS Update Threshold= 0.02
Bed Roughness Predictor= 0
Hydraulics Update Threshold= 0.02
Energy Slope Method= 1
Volume Change Method= 1
Sediment Retention Method= 0
Sediment TS Multiplier= 1
Warm Up Method= 0
XS Weighting Method= 0
Number of US Weighted Cross Sections= 1
Number of DS Weighted Cross Sections= 1
Upstream XS Weight=0
Main XS Weight=1
Downstream XS Weight=0
Number of DS XS's Weighted with US Boundary= 1
Upstream Boundary Weight= 1
Weight of XSs Associated with US Boundary= 0
Number of US XS's Weighted with DS Boundary= 1
Downstream Boundary Weight= 0.5
Weight of XSs Associated with DS Boundary= 0.5
Percentile Method= 0
Sediment Output Level= 3
Mass or Volume Output= 0
Output Increment Type= 1
Profile and TS Output Increment= 1
Transport Output Increment 1
XS Output Flag= 0
XS Output Increment= 10
Read HDF5 Sediment Hotstart= 0
Sediment Hotstart Type= 0
Write Gradation File= 0
Read Gradation Hotstart= 0
Write HDF5 File= 1
Write Binary Output= 1
Write DSS Sediment File= 0
DSS Sediment Output Type= 1
SV Curve= 0
Specific Gage Flag= 0
Subcell Erosion Methods= 0
Subcell Deposition Methods= 0
Advection Scheme= 1
Matrix Solver= 0
Implicit Weighting Factor= 1
Maximum Outer Loop Convergence Iterations= 5
Convergence Maximum Absolute= 0.001
Convergence RMSE= 0.0001
Grain Fractions Max Abs Error= 0.001
Max Subgrid Regions= 1
Max Subgrid Length Scale= 3.402823E+38
Initial Layer Thickness= 3.402823E+38
Min Layer Thickness= 3.402823E+38
Max Layer Thickness= 3.402823E+38
Number of Layers= 5

--- REDRN_2.f01 (steady flow) ---

Flow Title=Flow
Program Version=6.20
Number of Profiles= 1
Profile Names=P100yr
River Rch & RM=REDRN_2,Main            ,13549
     393
River Rch & RM=REDRN_2,Main            ,8662
     693
River Rch & RM=REDRN_2,Main            ,7647
     784
River Rch & RM=REDRN_2,Main            ,4203
     894
Boundary for River Rch & Prof#=REDRN_2,Main            , 1
Up Type= 0
Dn Type= 3
Dn Slope=0.05633
DSS Import GetInterval= 0
DSS Import GetPeak= 0
DSS Import FillOption= 0

--- REDRN_2.g01 (geometry) ---

Geom Title=Geometry
Program Version=6.20

River Reach=REDRN_2         ,Main
Reach XY= 30
      2280884.66      595716.412     2281268.702      595686.941
     2281732.504      595353.087     2281853.598      595419.493
     2282224.171      595051.264     2282350.733      595111.681
     2282630.942       594517.67     2283056.983      594248.399
     2283197.088      593973.139     2283134.327      593709.076
     2283345.758       593493.38     2283467.683      593540.135
     2283797.039      593126.843     2284073.731      593169.161
     2284176.704       592999.89     2284303.657      593159.395
     2284961.064      593140.446     2285121.383      593304.344
     2285233.933       593157.38     2285353.679      593290.038
     2285493.653      593211.913     2285519.695      593447.373
     2285862.577      593337.781     2285801.684      593611.162
     2286522.869      593863.538     2286939.572      594633.727
     2287056.617      594482.847     2287484.105      594808.243
     2287418.573       595063.72     2288410.163      596110.165

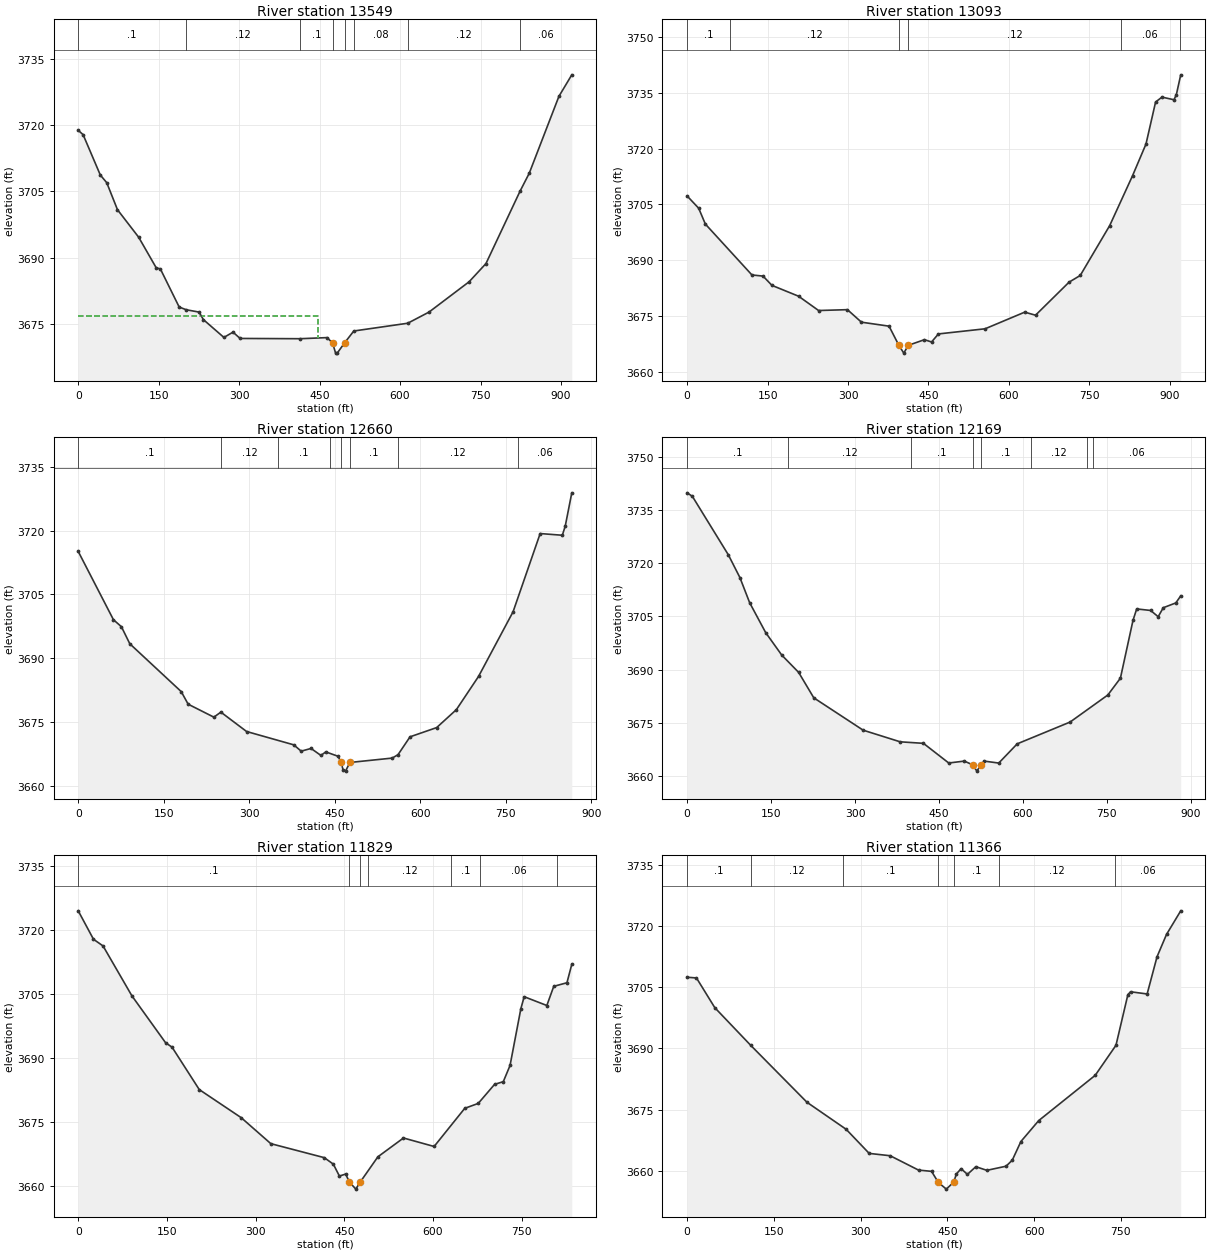
Type RM Length L Ch R = 1 ,13549   ,445.6,455.7,448.9
XS GIS Cut Line= 3
 2281009.8066023596174.2889409942280999.21249813595941.016064036
2280767.65831111595294.583885824
#Sta/Elev= 30
       0 3718.86     9.1 3717.88    41.2 3708.72    53.2 3706.98    73.2 3700.85
   112.7 3694.61   145.3  3687.7   153.3 3687.39   188.2 3678.78   201.3 3678.16
   225.3 3677.63   233.4 3675.92   271.6 3671.88   288.6 3673.08   301.8 3671.65
   413.6 3671.59   464.1 3671.84474.31753670.579   479.8 3668.34   482.9 3668.32
   496.8 3670.68   513.8 3673.34   614.3  3675.1     654 3677.63   728.8 3684.51
   760.2 3688.64   823.7 3705.05   840.9 3709.13   896.2 3726.57   920.2 3731.45
#Mann= 8 ,-1,0
       0      .1       0   201.3     .12       0   413.6      .1       0
474.3175    .045       0   496.8      .1       0   513.8     .08       0
   614.3     .12       0   823.7     .06       0
#XS Ineff= 2 , 0
          446.21 3676.83
Permanent Ineff=
       T       F
Bank Sta=474.3175,496.8
XS Rating Curve= 0 ,0
Exp/Cntr=0.3,0.1

Type RM Length L Ch R = 1 ,13093   ,432.1,433.9,432.6
XS GIS Cut Line= 3
2281415.49713727596045.9017789992281338.18272806595757.485031101
2281093.77087366 595185.67486559
#Sta/Elev= 30
       0 3707.27    21.5 3703.97    33.9 3699.72   120.8 3686.01   141.5 3685.71
   158.1 3683.21   207.8 3680.29   245.1 3676.44   298.9 3676.67     325  3673.3
   376.5 3672.23  394.83 3667.07     404 3664.97   412.43667.071   442.5 3668.59
   455.8 3667.97   468.6 3670.14   555.6 3671.52   629.5    3676   649.7 3675.18
   712.2 3684.07   733.1 3685.88     788  3699.3   830.6 3712.72   855.7 3721.26
   873.6 3732.57   885.5 3733.89   907.9 3733.18   912.3 3734.54   920.5 3739.89
#Mann= 6 ,-1,0
       0      .1       0      80     .12       0  394.83    .045       0
   412.4     .12       0   808.6     .06       0   918.6      .1       0
Bank Sta=394.83,412.4
XS Rating Curve= 0 ,0
Exp/Cntr=0.3,0.1

Type RM Length L Ch R = 1 ,12660   ,486.7,490.8,486.7
XS GIS Cut Line= 4
2281754.10280307595919.8343976992281747.86608583595910.909351394
2281671.87417318595568.6684490332281480.52611034595101.843311108
#Sta/Elev= 30
       0 3715.14    61.8 3699.06    75.8 3697.41    90.5  3693.4   180.7 3682.14
   192.9 3679.17     238 3676.12   250.3  3677.3   295.4 3672.74   378.2  3669.6
   391.2 3668.11   408.5 3668.75   425.8 3667.11   434.4 3667.94     456  3666.9
  461.293665.453   464.7 3663.73     469 3663.41   476.7 3665.45   550.9 3666.48
   561.1 3667.28   582.2 3671.49   628.9 3673.66   663.5 3677.89   702.4 3685.71
     763 3700.94   810.5 3719.35   849.4 3718.95   854.5  3721.1     866 3728.94
#Mann= 8 ,-1,0
       0      .1       0  250.89     .12       0  350.89      .1       0
  441.46     .12       0  461.29    .045       0   476.7      .1       0
  561.46     .12       0  771.46     .06       0
Bank Sta=461.29,476.7
XS Rating Curve= 0 ,0
Exp/Cntr=0.3,0.1

Type RM Length L Ch R = 1 ,12169   ,335.9,340.1,331.2
XS GIS Cut Line= 3
2282147.04963372 595742.645110342281943.58737395595302.374511875
2281762.09097241594949.348822982
#Sta/Elev= 30
       0 3739.78     9.3 3738.79    73.6 3722.33    94.2 3715.95   111.7 3708.85
   140.3 3700.45     169 3694.13   199.2 3689.26   226.3 3682.09   314.5 3672.99
   380.6 3669.72   422.2 3669.29   467.4 3663.76   495.3 3664.29     510 3663.26
   517.8 3661.47  525.063663.299   531.3 3664.28   556.8 3663.74   589.8 3669.15
   684.3 3675.28   751.7 3682.89   774.2 3687.62   796.7  3703.9   803.3 3707.11
   828.2 3706.68   841.7 3704.92   850.8 3707.45   873.2  3708.8     882 3710.79
#Mann= 8 ,-1,0
       0      .1       0     180     .12       0     400      .1       0
     510    .045       0  525.06      .1       0  615.01     .12       0
  715.01      .1       0  725.01     .06       0
Bank Sta=510,525.06
XS Rating Curve= 0 ,0
Exp/Cntr=0.3,0.1

Type RM Length L Ch R = 1 ,11829   ,458.3,462.7,452.3
XS GIS Cut Line= 2
2282470.42718923595475.3655751762281890.37119233594875.238436517
#Sta/Elev= 30
       0 3724.42    25.8 3717.76      42 3716.19    90.8  3704.5   147.7 3693.52
   158.7 3692.47   204.7 3682.54   275.6 3675.96   325.7 3669.87   416.1 3666.59
   431.4 3665.07   441.6 3662.29   452.2 3662.74   458.6 3660.88   469.4 3659.22
   476.83660.866   506.7 3666.79     550  3671.2   601.8 3669.21   653.6 3678.15
   676.4  3679.3     704 3683.76   718.8  3684.4   730.2  3688.2   748.5 3701.51
   754.1  3704.3   792.4 3702.24   804.1 3706.73   826.4 3707.57   834.6 3711.89
#Mann= 7 ,-1,0
       0      .1       0   458.6    .045       0   476.8      .1       0
     490     .12       0     630      .1       0     680     .06       0
     810      .1       0
Bank Sta=458.6,476.8
XS Rating Curve= 0 ,0
Exp/Cntr(USF)=0,0
Exp/Cntr=0.3,0.1

Type RM Length L Ch R = 1 ,11366   ,569.1,580.2,563.1
XS GIS Cut Line= 2
2282749.41605971595258.5972441552282085.06126742594722.697759131
#Sta/Elev= 30
       0 3707.46    16.1 3707.29    47.8    3700     110 3690.75   207.2  3676.8
     275 3670.17   314.8 3664.26   351.1 3663.69   400.1 3660.17   422.7 3659.86
   434.3 3657.15   448.2  3655.5     461 3657.23   465.6 3659.21   473.7 3660.52
   484.7 3659.12   499.2    3661   518.3 3660.11   551.5 3661.12   562.3 3662.61
   577.2 3667.18     608 3672.31   705.7 3683.41   741.6 3690.78   762.2  3703.2
   766.8  3703.9   795.5 3703.36   812.6 3712.48     829 3717.96   853.6 3723.75
#Mann= 7 ,-1,0
       0      .1       0     110     .12       0     270      .1       0
   434.3    .045       0     461      .1       0     540     .12       0
     740     .06       0
Bank Sta=434.3,461
XS Rating Curve= 0 ,0
Exp/Cntr(USF)=0,0
Exp/Cntr=0.3,0.1

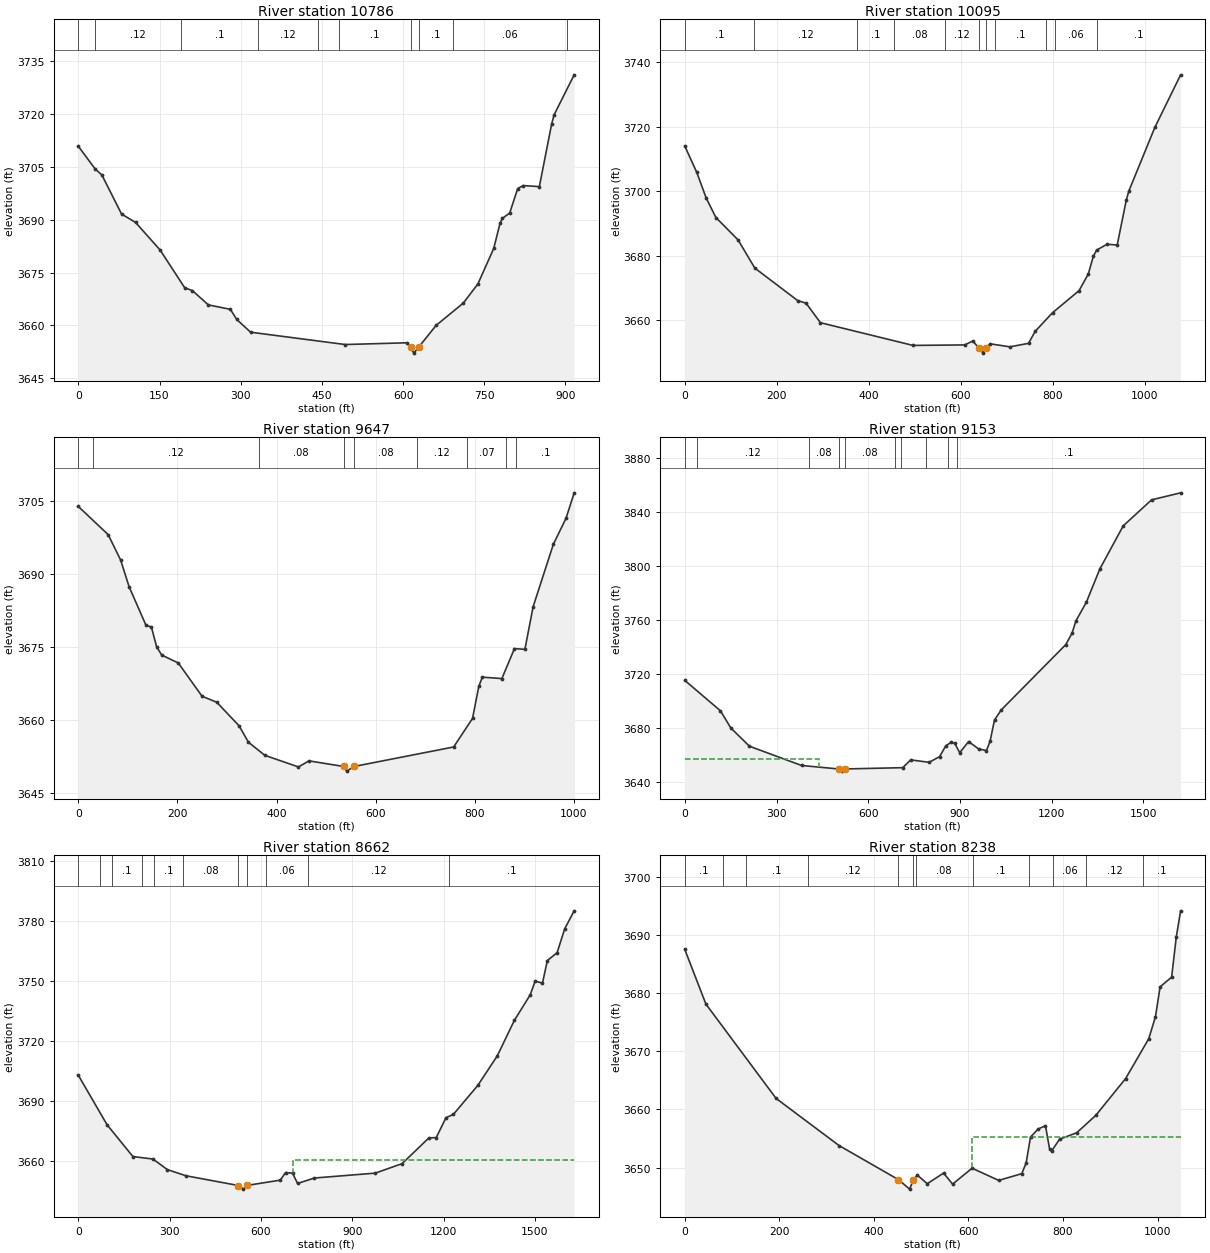
Type RM Length L Ch R = 1 ,10786   ,682.7,691,683.4
XS GIS Cut Line= 3
2283050.76879156595008.0292911942282839.40203983594778.035570881
2282307.47084673594492.601003836
#Sta/Elev= 30
       0 3710.85      31 3704.41    43.5 3702.69    79.9 3691.59   105.8 3689.21
   151.1 3681.39   196.4  3670.7   210.7 3669.86   240.3 3665.81   280.9 3664.55
   292.6 3661.68   318.3 3658.06   493.1 3654.56   607.9 3655.06  613.913653.747
   619.7 3652.12   628.5 3653.77     661    3660   711.3 3666.34   738.2 3671.77
   767.4 3681.83   779.2 3689.04   783.6  3690.4   796.9 3691.88   811.7 3698.84
   821.8 3699.68   851.7 3699.39   874.4 3717.15   878.9 3719.75     916 3731.12
#Mann= 10 ,-1,0
       0      .1       0      30     .12       0     190      .1       0
  332.37     .12       0  442.37     .08       0  482.37      .1       0
  613.91    .045       0   628.5      .1       0  692.37     .06       0
  902.37      .1       0
Bank Sta=613.91,628.5
XS Rating Curve= 0 ,0
Exp/Cntr=0.3,0.1

Type RM Length L Ch R = 1 ,10095   ,443.8,447.9,441.1
XS GIS Cut Line= 4
2283277.89670881594800.9490237492283155.69458312594532.780390027
2282570.78289804594236.9761285112282444.85766514594218.432071248
#Sta/Elev= 30
       0 3713.96    26.1 3705.78    46.4 3697.89    67.6 3691.83   115.9 3684.87
   152.1 3676.17   245.3  3666.1   263.5  3665.3   294.7 3659.25   495.9 3652.21
   607.9 3652.36   625.9 3653.57   639.1 3651.39   648.3 3649.82  655.42 3651.45
   663.2 3652.71   706.5 3651.77   746.9 3652.85   761.4 3656.58     799 3662.33
   856.7 3669.17   876.9 3674.37   887.7 3679.83   894.8 3681.72   917.2 3683.53
   939.6 3683.32   959.3 3697.19   964.9 3700.04  1021.5 3719.78  1077.4 3736.03
#Mann= 11 ,-1,0
       0      .1       0     150     .12       0   374.7      .1       0
   454.7     .08       0   564.7     .12       0   639.1    .045       0
  655.42     .12       0   674.7      .1       0   784.7     .07       0
   804.7     .06       0   894.7      .1       0
Bank Sta=639.1,655.42
XS Rating Curve= 0 ,0
Exp/Cntr=0.3,0.1

Type RM Length L Ch R = 1 ,9647    ,481.7,493.9,484.2
XS GIS Cut Line= 4
2283530.18347422594343.3531798452283395.70682442594232.961900158
2282697.23109113593992.1081990242282610.92518156594008.165112433
#Sta/Elev= 30
       0 3703.97    60.2 3698.18    85.4 3692.94   102.4 3687.46   136.5 3679.53
   147.5 3679.16   157.9 3675.11   168.2  3673.4   201.8 3671.75   249.6 3664.92
   279.3 3663.68   324.5 3658.82   343.3 3655.44   376.6 3652.74   444.3 3650.36
   465.4 3651.61   535.3 3650.46   541.6  3649.5  557.243650.476   757.4 3654.47
   795.5 3660.34   808.2 3666.94   815.3 3668.84   854.7 3668.55   880.1 3674.71
   901.2 3674.57   917.8 3683.34   958.6 3696.18   984.3 3701.57  1000.6 3706.78
#Mann= 9 ,-1,0
       0      .1       0      30     .12       0  363.98     .08       0
   535.3    .045       0  557.24     .08       0  683.98     .12       0
  783.98     .07       0  863.98     .06       0  883.98      .1       0
Bank Sta=535.3,557.24
XS Rating Curve= 0 ,0
Exp/Cntr(USF)=0,0
Exp/Cntr=0.3,0.1

Type RM Length L Ch R = 1 ,9153    ,471.6,490.8,481
XS GIS Cut Line= 4
2283639.54613354594088.7279139962283445.80066497593969.320609032
2282933.45446225593790.9487074772282108.04600167594001.371967994
#Sta/Elev= 30
       0 3715.19   116.7 3692.64   150.4 3679.98   211.4 3666.41   381.8 3652.16
   504.6 3649.52   513.1 3647.96  523.96 3649.57   712.8 3650.52     739 3656.29
   799.3 3654.49   833.3 3658.68     854 3666.78   870.5 3669.19   882.9 3668.59
   899.4 3661.61   928.3 3669.88   961.3 3664.35   986.8 3663.24   998.5 3670.01
  1013.1 3685.85  1035.6 3693.43  1246.1 3741.68  1266.8 3750.19  1279.5 3759.34
  1313.5 3773.06  1357.6 3797.76  1434.1 3829.69  1526.8 3848.94  1621.9 3854.16
#Mann= 10 ,-1,0
       0      .1       0      40     .12       0  407.59     .08       0
   504.6    .045       0  523.96     .08       0  687.59     .06       0
  707.59     .08       0  790.09      .1       0  860.09     .06       0
  890.09      .1       0
#XS Ineff= 2 , 0
          438.19 3656.98
Permanent Ineff=
       F       F
Bank Sta=504.6,523.96
XS Rating Curve= 0 ,0
Exp/Cntr=0.3,0.1

Type RM Length L Ch R = 1 ,8662    ,415.5,423.8,419.4
XS GIS Cut Line= 4
2283688.61920077593955.7415118752283465.44662221593733.004701134
2282998.29821755593247.4688396842282950.74230029592609.303676689
#Sta/Elev= 30
       0 3702.97    94.2 3678.23   179.2 3662.28   245.4 3661.01   292.4 3655.73
   353.9 3652.64   526.23647.763   542.6 3645.96   553.7 3647.81   663.3 3650.45
     681 3654.25   703.7 3653.96   720.3  3648.8   775.8 3651.52   975.6 3653.97
  1063.6 3658.72  1151.8 3671.61  1175.9 3671.76    1208 3681.75    1232 3683.34
  1312.3 3697.86  1376.4 3712.67  1432.6 3730.47  1484.7 3743.24  1500.8  3750.1
  1524.9 3749.08  1540.9 3760.37    1573 3764.33  1597.9 3776.25    1629 3785.29
#Mann= 11 ,-1,0
       0      .1       0      70     .12       0     110      .1       0
     210     .12       0     250      .1       0  345.31     .08       0
   526.2    .045       0   553.7     .07       0  615.31     .06       0
  755.31     .12       0 1219.08      .1       0
#XS Ineff= 2 , 0
                           705.7         3660.41
Permanent Ineff=
       F       F
Bank Sta=526.2,553.7
XS Rating Curve= 0 ,0
Exp/Cntr=0.3,0.1

Type RM Length L Ch R = 1 ,8238    ,576.6,591.5,582.6
XS GIS Cut Line= 3
2283850.86957855593818.4077915612283675.34748429593552.284527952
2283257.60071648592953.598145597
#Sta/Elev= 30
       0  3687.5    44.6 3678.12   193.1 3661.89   326.2 3653.79  451.95 3647.92
   475.6 3646.29   483.5  3647.9   492.1 3648.68   512.9 3647.22   547.4 3649.05
   566.5 3647.15   607.7 3649.89     664 3647.79   712.8 3648.95     722 3650.79
   731.3 3655.24   746.9  3656.6   762.9 3657.21   771.5 3653.25   776.2 3652.87
   792.7 3654.88   828.9 3655.98   869.2 3658.96   932.5 3665.31   981.4 3672.16
   995.6 3675.94  1005.4 3681.08  1029.8 3682.75  1039.6 3689.65  1048.8 3694.15
#Mann= 12 ,-1,0
       0      .1       0      80     .12       0     130      .1       0
     260     .12       0  451.95    .045       0   483.5     .12       0
  488.79     .08       0  608.79      .1       0  728.79     .08       0
  778.79     .06       0  848.79     .12       0  968.79      .1       0
#XS Ineff= 2 , 0
                          607.01          3655.2
Permanent Ineff=
       F       F
Bank Sta=451.95,483.5
XS Rating Curve= 0 ,0
Exp/Cntr=0.3,0.1

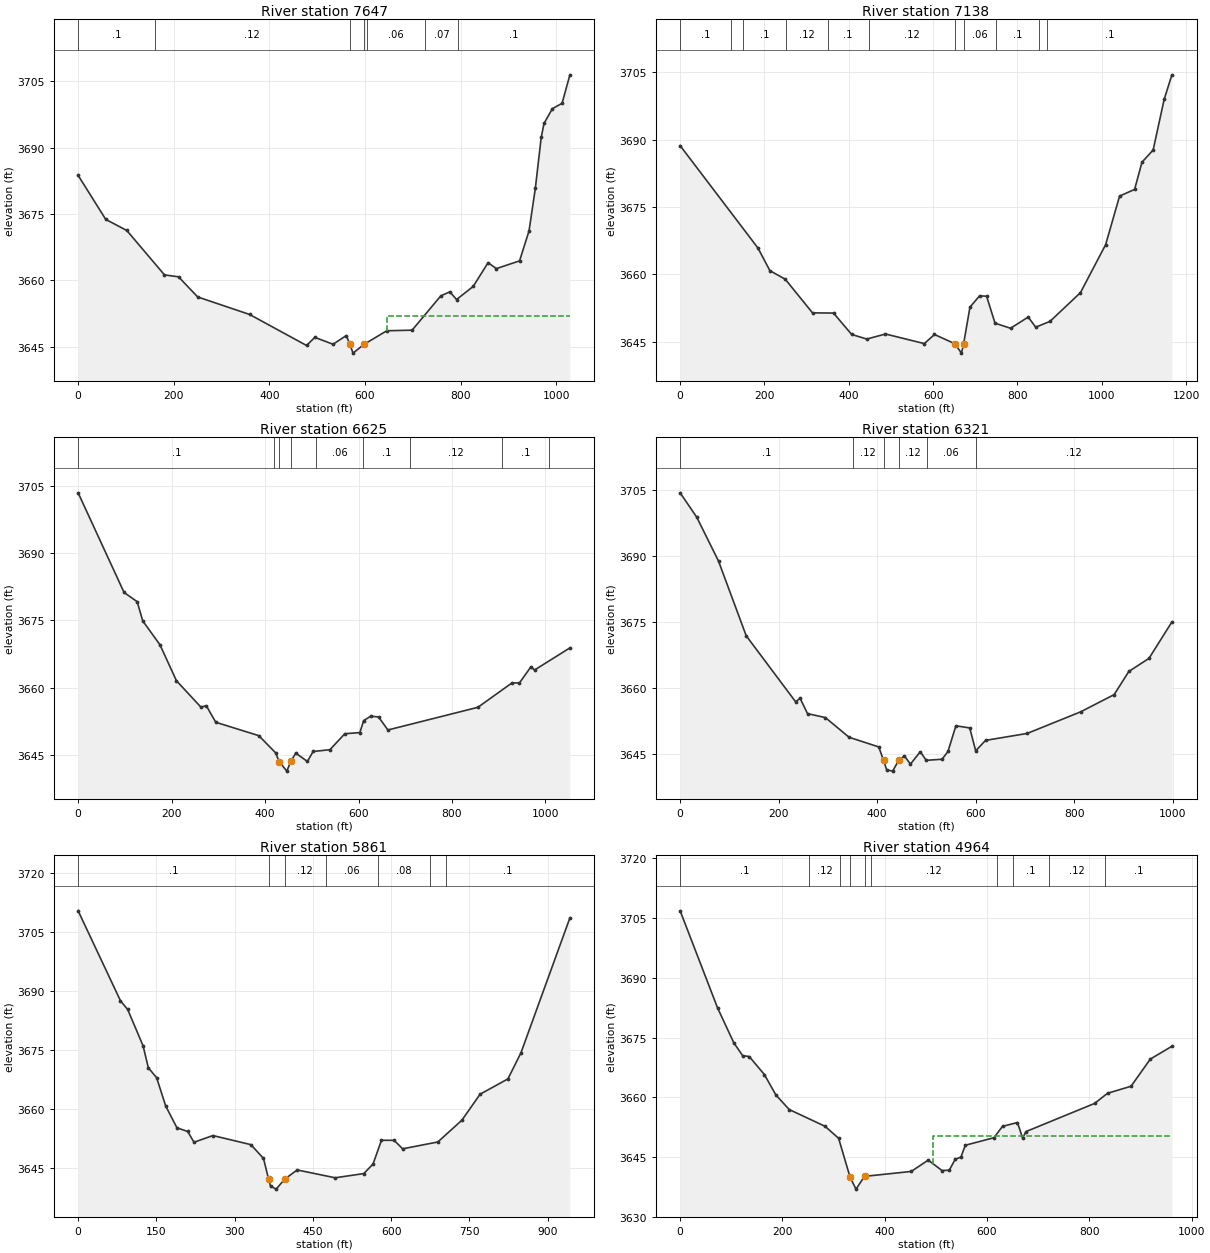
Type RM Length L Ch R = 1 ,7647    ,487.8,508.8,507
XS GIS Cut Line= 3
2284095.87676372593674.8449174962284080.14056037593399.999161005
2283683.09348555592759.691730137
#Sta/Elev= 30
       0 3683.73    57.8 3673.77   101.8 3671.27   180.6 3661.23     210 3660.79
   250.1 3656.24   358.7 3652.28   477.8 3645.27   495.1  3647.1   533.3 3645.55
     561 3647.51  568.463645.497   575.1 3643.54  597.82 3645.51   645.7  3648.6
   698.6 3648.73   758.7 3656.49   777.5  3657.4   791.6 3655.66   826.4 3658.62
   857.5 3663.98   874.9 3662.65   923.4  3664.4   943.2 3671.17   956.4  3680.8
   968.7 3692.32   974.6 3695.48     992  3698.8  1012.3 3700.02  1028.7 3706.46
#Mann= 7 ,-1,0
       0      .1       0     160     .12       0  568.46    .045       0
  597.82     .12       0   605.3     .06       0   725.3     .07       0
   795.3      .1       0
#XS Ineff= 2 , 0
                          646.19         3651.91
Permanent Ineff=
       F       F
Bank Sta=568.46,597.82
XS Rating Curve= 0 ,0
Exp/Cntr=0.3,0.1

Type RM Length L Ch R = 1 ,7138    ,501.3,512.5,502.6
XS GIS Cut Line= 4
2284218.87142737593659.7113558452284163.37766815593286.532171139
 2284184.4810748592954.4741795942283909.31351498592590.583574716
#Sta/Elev= 30
       0 3688.68   184.5 3665.89   212.8 3660.86   249.2 3658.95   313.9 3651.46
   363.7 3651.42   406.7 3646.66   442.8 3645.63   486.9 3646.76   579.1 3644.62
   603.1 3646.65   651.2  3644.6   667.2  3642.5  672.22 3644.58   687.3 3652.74
     710 3655.24   726.7 3655.18   746.7 3649.17   783.5 3648.03   825.4 3650.53
   843.2 3648.27   877.1 3649.57   949.3 3655.96    1009 3666.63  1042.1 3677.45
  1077.7 3678.94  1095.2 3684.99  1121.7 3687.72  1147.9 3699.01  1166.2 3704.44
#Mann= 11 ,-1,0
       0      .1       0     120     .12       0     150      .1       0
     250     .12       0     350      .1       0  447.28     .12       0
   651.2    .045       0  672.22     .06       0  750.01      .1       0
  850.01     .06       0  870.01      .1       0
Bank Sta=651.2,672.22
XS Rating Curve= 0 ,0
Exp/Cntr=0.3,0.1

Type RM Length L Ch R = 1 ,6625    ,302.7,304,303.9
XS GIS Cut Line= 3
2284479.00100767593631.3707716482284518.38894483592805.375192361
2284552.54809043  592582.5143502
#Sta/Elev= 30
       0 3703.37    98.3 3681.19   126.3 3679.14   138.3 3674.86   175.2 3669.52
   210.4 3661.53   262.5 3655.69   274.5 3655.94   294.5 3652.29   386.6 3649.31
   422.7 3645.48     430 3643.55   446.6 3641.41   455.2  3643.6   465.7 3645.41
   490.7 3643.56   502.8 3645.78   538.8 3646.18   570.8 3649.74   602.9 3649.99
     611 3652.66   626.2 3653.64   642.9 3653.48   662.9 3650.57   855.5 3655.62
   928.3 3661.04   944.5 3661.06   968.8 3664.61   976.9 3663.93  1052.4 3668.85
#Mann= 9 ,-1,0
       0      .1       0     420     .12       0     430    .045       0
   455.2     .12       0     510     .06       0     610      .1       0
     710     .12       0  906.93      .1       0 1006.93     .12       0
Bank Sta=430,455.2
XS Rating Curve= 0 ,0
Exp/Cntr=0.3,0.1

Type RM Length L Ch R = 1 ,6321    ,456.7,460.1,456.8
XS GIS Cut Line= 3
2284762.55157836593614.7707339142284838.82191705592723.612039717
2284899.03534233 592639.31324432
#Sta/Elev= 30
       0  3704.3    33.7 3698.77    77.9  3688.8   134.1 3671.85   234.4 3656.86
   243.4 3657.67   258.5 3654.18   294.7 3653.29   342.8 3648.82   403.1 3646.62
  412.813643.548   419.1 3641.43   431.2 3641.13   443.4 3643.55   455.2 3644.58
   467.3 3642.72   487.4 3645.53   499.4 3643.58   531.5 3643.83   543.6  3645.6
   559.6 3651.42   587.7 3650.93   599.8 3645.73   619.8 3648.11   704.2 3649.68
   812.6 3654.58   880.8  3658.5   910.5 3663.75   951.5 3666.73     998    3675
#Mann= 6 ,-1,0
       0      .1       0     350     .12       0  412.81    .045       0
   443.4     .12       0     500     .06       0     600     .12       0
Bank Sta=412.81,443.4
XS Rating Curve= 0 ,0
Exp/Cntr(USF)=0,0
Exp/Cntr=0.3,0.1

Type RM Length L Ch R = 1 ,5861    ,873.5,897.4,886.1
XS GIS Cut Line= 4
2285043.12472031593672.1301180122285117.81078753 593492.33676917
2285190.30697625592964.8701532692285281.17723219592769.468169346
#Sta/Elev= 30
       0  3710.4    81.2 3687.48    94.9 3685.29   124.5 3676.01   134.6 3670.41
   150.5 3667.88   167.8  3660.7   189.4 3655.13     210  3654.2   222.1 3651.45
   258.4 3653.16   331.1 3650.84   355.3 3647.33  365.033642.069   368.8 3640.27
   379.6 3639.51   395.7 3642.03   419.9  3644.4   492.6  3642.4   547.5 3643.47
   565.3 3645.91   581.4 3651.96   605.7 3651.94     622 3649.78   689.5 3651.52
   735.6 3657.07   770.4 3663.68   823.8 3667.59   848.7 3674.21   942.6 3708.61
#Mann= 7 ,-1,0
       0      .1       0  365.03    .045       0   395.7     .12       0
  474.69     .06       0  574.69     .08       0  674.69     .12       0
  704.69      .1       0
Bank Sta=365.03,395.7
XS Rating Curve= 0 ,0
Exp/Cntr=0.3,0.1

Type RM Length L Ch R = 1 ,4964    ,758,761.4,746.6
XS GIS Cut Line= 4
2285348.98485057 593741.730515712285442.96328406 593518.42925346
2285669.19347662593228.2064919612285773.56577165592892.876685057
#Sta/Elev= 30
       0 3706.82    73.1 3682.48   104.8 3673.73   122.1 3670.49   135.1 3670.25
   164.7 3665.74   187.2 3660.61   213.2 3656.96   283.3 3652.75   309.8 3649.74
  332.143640.007   343.8 3636.98   360.5 3640.18   451.8 3641.42     485 3644.26
   511.9 3641.65   526.2 3641.73   537.6 3644.44     549 3645.04   557.5 3647.99
   613.4 3649.88   630.2 3652.73   659.5  3653.7   669.4 3649.81   676.3 3651.43
   810.3 3658.49   835.5 3661.03   881.5  3662.8   919.2 3669.62   961.4 3672.83
#Mann= 10 ,-1,0
       0      .1       0  252.27     .12       0  312.27      .1       0
  332.14    .045       0   360.5      .1       0  372.27     .12       0
  620.25     .08       0  650.25      .1       0  720.25     .12       0
  830.25      .1       0
#XS Ineff= 2 , 0
                          494.58         3650.28
Permanent Ineff=
       F       F
Bank Sta=332.14,360.5
XS Rating Curve= 0 ,0
Exp/Cntr=0.3,0.1

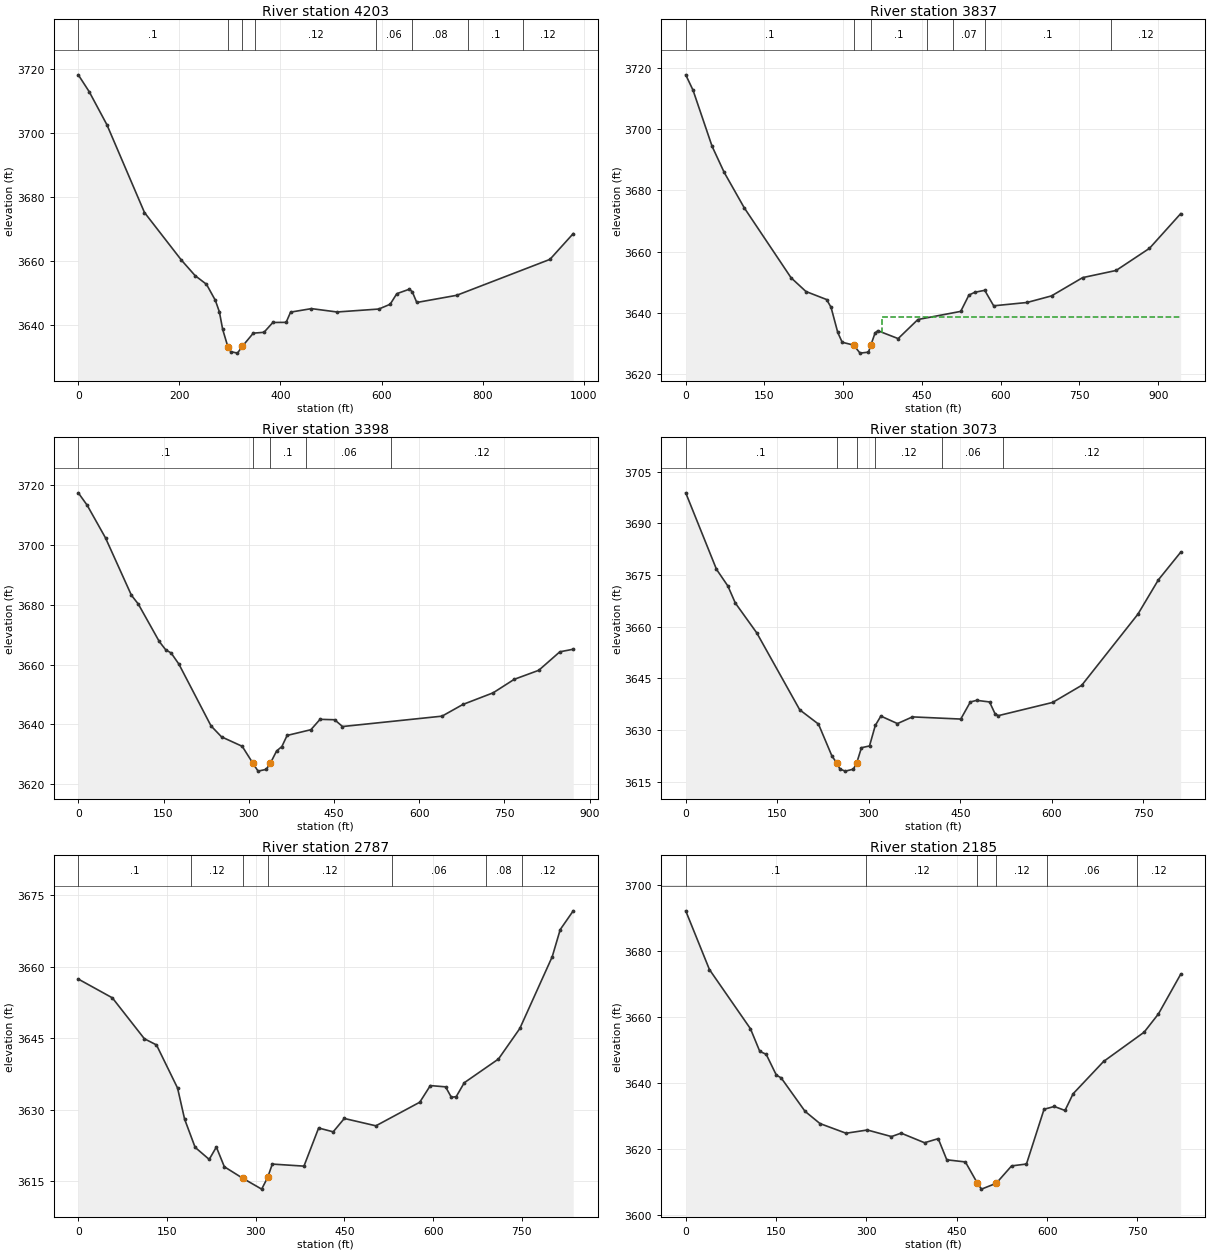
Type RM Length L Ch R = 1 ,4203    ,366.1,365.6,364.1
XS GIS Cut Line= 3
2285734.55126744593920.8709249162285991.22034253593344.883046764
2286135.19544063593027.182472048
#Sta/Elev= 30
       0 3718.12    21.6 3712.85    56.6 3702.53     131 3675.08     204 3660.22
   231.2 3655.36   253.7 3652.65   271.2 3647.64   279.2 3644.04   285.7 3638.57
  295.86 3633.19   301.8  3631.6     315 3631.14  324.483633.242   346.3 3637.38
   367.5 3637.65     385 3640.72   411.3 3640.76   420.1 3643.95   461.4 3645.05
     512    3644   594.7 3644.92   617.1 3646.41   630.3 3649.72   655.3 3651.13
     661 3650.28   669.8 3646.97   748.8 3649.21   933.3 3660.44   979.4  3668.5
#Mann= 8 ,-1,0
       0      .1       0  295.86    .045       0  324.48      .1       0
     350     .12       0     590     .06       0  660.59     .08       0
  770.59      .1       0  880.59     .12       0
Bank Sta=295.86,324.48
XS Rating Curve= 0 ,0
Exp/Cntr=0.3,0.1

Type RM Length L Ch R = 1 ,3837    ,425.2,439.5,446.9
XS GIS Cut Line= 2
2286101.29673383594046.3002817792286414.40654531593157.148701759
#Sta/Elev= 30
       0 3717.69    13.9 3712.69    50.2 3694.39    73.3 3685.87   111.4 3674.35
   200.7 3651.51     229 3647.04   268.4 3644.42   276.8 3641.88   289.6 3633.68
     298  3630.5   319.9 3629.56     332 3626.95   348.1 3627.27  352.613629.586
   360.7 3633.54   365.9 3634.26   404.6 3631.69   442.2 3637.91   523.8 3640.56
   539.4 3645.88   550.6 3646.79   569.5 3647.43   586.5 3642.38     650 3643.46
   696.7 3645.61     756 3651.57   819.7  3653.9   883.3 3661.12   942.7 3672.42
#Mann= 7 ,-1,0
       0      .1       0   319.9    .045       0  352.61      .1       0
     460     .06       0     510     .07       0     570      .1       0
     810     .12       0
#XS Ineff= 2 , 0
                          374.73         3638.79
Permanent Ineff=
       F       F
Bank Sta=319.9,352.61
XS Rating Curve= 0 ,0
Exp/Cntr(USF)=0,0
Exp/Cntr=0.3,0.1

Type RM Length L Ch R = 1 ,3398    ,322.5,324.2,325.9
XS GIS Cut Line= 3
2286374.22626949594196.9572809072286524.79782499593972.037057263
2287041.50816804593666.275242667
#Sta/Elev= 30
       0  3717.4    15.7 3713.23    47.9 3702.33    93.5 3683.16   105.6 3680.22
   142.5  3667.7   153.8 3664.93   163.4 3663.85   177.1 3660.12   233.6 3639.48
   252.1 3635.81   288.5 3632.65   307.3 3626.99   316.4 3624.35   330.7 3624.93
  337.973626.954     349 3631.08   358.3 3632.57   367.5 3636.28   409.4  3638.2
   425.5 3641.67   451.2 3641.53     465 3639.26   640.2 3642.73   676.9 3646.64
   730.1 3650.53   767.3 3655.05   810.4 3658.06   847.5 3664.24   871.1 3665.11
#Mann= 5 ,-1,0
       0      .1       0   307.3    .045       0  337.97      .1       0
  400.67     .06       0  550.67     .12       0
Bank Sta=307.3,337.97
XS Rating Curve= 0 ,0
Exp/Cntr(USF)=0,0
Exp/Cntr=0.3,0.1

Type RM Length L Ch R = 1 ,3073    ,286.6,285.9,285
XS GIS Cut Line= 2
2286486.30098811594338.9188263642287223.87585998594002.003342869
#Sta/Elev= 30
       0 3698.84    50.4 3676.66    69.1 3671.81    81.2  3666.9   116.4 3658.22
   186.8 3635.91   217.5 3631.77   239.5 3622.53   247.2 3620.56   252.7 3618.71
   261.5 3618.13   274.7  3618.7  280.233620.577   287.9 3624.92   301.1 3625.43
   310.6 3631.39   319.7 3634.09   346.9 3631.92   371.5 3633.86   450.6 3633.23
   466.3 3638.18   476.7 3638.66   497.8 3638.19   506.8 3634.76   512.2 3634.22
   601.1 3638.05   648.7    3643   740.8 3663.64   774.4 3673.61   810.9 3681.61
#Mann= 6 ,-1,0
       0      .1       0   247.2    .045       0  280.23      .1       0
     310     .12       0     420     .06       0     520     .12       0
Bank Sta=247.2,280.23
XS Rating Curve= 0 ,0
Exp/Cntr(USF)=0,0
Exp/Cntr=0.3,0.1

Type RM Length L Ch R = 1 ,2787    ,612,602,571.9
XS GIS Cut Line= 2
2286593.03970698 594620.334936152287335.67195214594234.969014335
#Sta/Elev= 30
       0 3657.37    57.6 3653.43   111.7 3644.86   132.2 3643.56   167.8 3634.53
   179.7 3628.02   197.5  3622.1   221.3 3619.57   233.4 3622.16   246.9 3618.03
   277.6 3615.65     310 3613.34  320.093615.778     328 3618.59   381.5 3618.16
   406.3 3626.15   430.9 3625.35   449.7 3628.15   503.1 3626.61   577.3 3631.56
   595.1 3635.04   620.9 3634.78   630.7 3632.58   638.9 3632.73   652.5 3635.64
   710.3 3640.61   746.4 3647.01   801.2 3662.06   814.7 3667.74   836.7 3671.67
#Mann= 7 ,-1,0
       0      .1       0     190     .12       0   277.6    .045       0
  320.09     .12       0     530     .06       0     690     .08       0
     750     .12       0
Bank Sta=277.6,320.09
XS Rating Curve= 0 ,0
Exp/Cntr(USF)=0,0
Exp/Cntr=0.3,0.1

Type RM Length L Ch R = 1 ,2185    ,333.6,334.1,333.7
XS GIS Cut Line= 2
2286856.67775521594921.3460615932287400.35414087594305.237656961
#Sta/Elev= 30
       0 3692.08    39.4 3674.27   107.5 3656.33   122.9  3649.5   133.6 3648.59
   150.4 3642.31   158.5 3641.43   198.1 3631.31   222.9  3627.6   266.2 3624.67
   301.5 3625.65   341.6 3623.66   357.6  3624.7   396.5 3621.79   419.2 3623.03
   433.4 3616.62   464.3 3615.97   484.4 3609.48     491 3607.73   515.5  3609.5
     541 3614.77   565.7 3615.34   594.9 3631.94   611.9 3632.78   629.7 3631.57
   643.1 3636.63   693.7 3646.42     761 3655.29   784.8 3660.84   821.7 3672.85
#Mann= 6 ,-1,0
       0      .1       0     300     .12       0   484.4    .045       0
   515.5     .12       0     600     .06       0     750     .12       0
Bank Sta=484.4,515.5
XS Rating Curve= 0 ,0
Exp/Cntr(USF)=0,0
Exp/Cntr=0.3,0.1

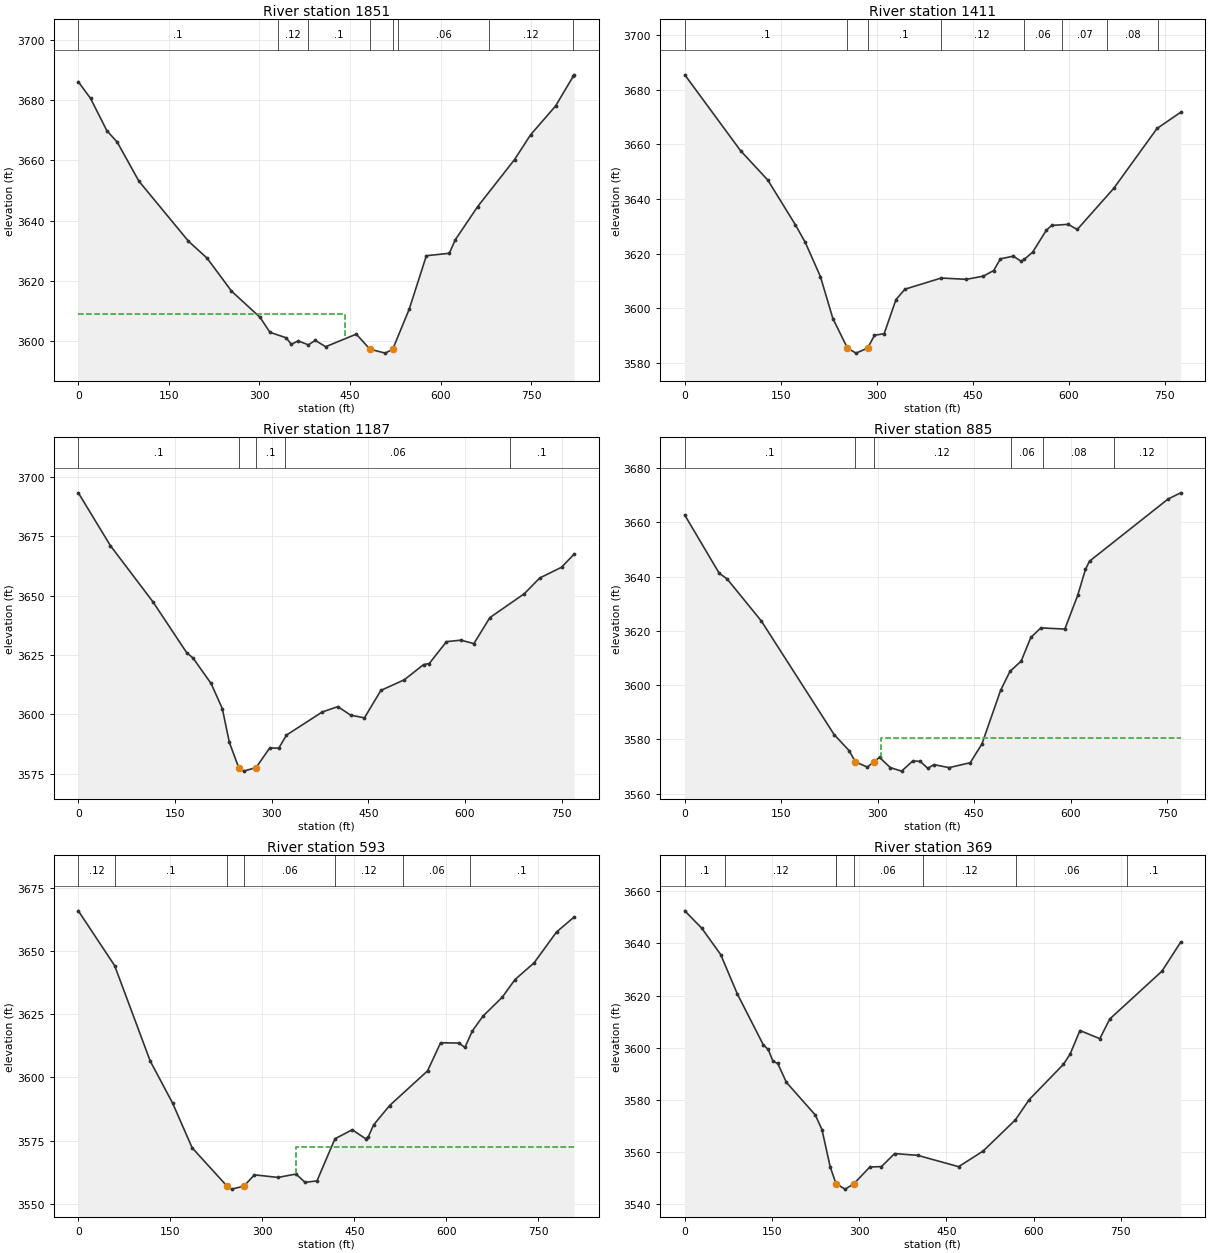
Type RM Length L Ch R = 1 ,1851    ,431.1,440.8,440.2
XS GIS Cut Line= 2
2287096.82536519595136.1632794122287648.78176362594528.007684048
#Sta/Elev= 30
       0 3686.04    20.2 3680.53    47.2 3669.85    64.5    3666   100.2 3653.13
   182.3 3633.21   213.3 3627.55   253.7 3616.64   301.1 3607.92   317.3 3602.98
   344.3 3601.15   352.8 3598.98   364.1 3600.12   381.1 3598.82   392.4  3600.3
   409.7  3598.2   460.4 3602.37     483 3597.38   508.5 3596.07   520.8 3597.38
   548.2 3610.72   576.5 3628.37   614.4 3629.17   624.6 3633.72   661.4 3644.64
   722.5 3660.23   749.2 3668.48   790.6 3678.03     820 3687.95   821.3 3688.34
#Mann= 8 ,-1,0
       0      .1       0     330     .12       0     380      .1       0
     483    .045       0   520.8      .1       0     530     .06       0
     680     .12       0     820      .1       0
#XS Ineff= 2 , 0
          441.16 3609.17
Permanent Ineff=
       F       F
Bank Sta=483,520.8
XS Rating Curve= 0 ,0
Exp/Cntr(USF)=0,0
Exp/Cntr=0.3,0.1

Type RM Length L Ch R = 1 ,1411    ,224,223.7,222.9
XS GIS Cut Line= 2
2287255.02218931595285.8334176462287834.82663013594771.779995883
#Sta/Elev= 30
       0 3685.54    87.1 3657.73   129.8 3646.92   172.6 3630.63   188.3 3624.07
     212 3611.51   231.4 3596.16   254.2 3585.31   267.6 3583.46  285.863585.317
   296.4    3590   311.6  3590.6     330 3603.09   344.1 3606.92   400.8 3611.01
   439.9 3610.53   466.6  3611.7   482.7 3613.75   493.3 3618.05   513.5 3619.02
   525.4 3617.19   530.8 3617.92   543.6 3620.48   565.2 3628.61   573.5  3630.3
   599.2  3630.7   613.3 3628.81   670.3 3643.88     738 3665.86   774.9 3671.79
#Mann= 8 ,-1,0
       0      .1       0   254.2    .045       0  285.86      .1       0
     400     .12       0     530     .06       0     590     .07       0
     660     .08       0     740     .12       0
Bank Sta=254.2,285.86
XS Rating Curve= 0 ,0
Exp/Cntr(USF)=0,0
Exp/Cntr=0.3,0.1

Type RM Length L Ch R = 1 ,1187    ,298.7,302,304.7
XS GIS Cut Line= 2
2287418.79812774595451.6164702632287974.69310709594919.630952392
#Sta/Elev= 30
       0 3693.41    49.8 3671.13   115.9 3647.41     168 3626.07   178.1 3623.73
     206 3613.03   223.4 3602.47   234.4 3588.17   248.8 3577.59   256.6 3576.08
  275.753577.566   296.9 3585.81   311.1  3585.8     323 3591.28   378.4    3601
   402.7 3603.28   422.7 3599.65     444 3598.55   469.5 3610.12   505.7 3614.57
   535.8    3621   544.5 3621.45   571.3 3630.67   593.6 3631.29   613.8 3629.84
   638.6  3640.8     692 3650.87   716.1 3657.53   749.8 3662.02   769.4  3667.6
#Mann= 5 ,-1,0
       0      .1       0   248.8    .045       0  275.75      .1       0
     320     .06       0     670      .1       0
Bank Sta=248.8,275.75
XS Rating Curve= 0 ,0
Exp/Cntr(USF)=0,0
Exp/Cntr=0.3,0.1

Type RM Length L Ch R = 1 ,885     ,292.2,291.9,290.2
BEGIN DESCRIPTION:
Area disconnected without IFA
END DESCRIPTION:
XS GIS Cut Line= 3
2287610.64659427595591.7781973912288042.17614214595324.832011968
2288210.77373293595122.113480179
#Sta/Elev= 30
       0 3662.71    53.5 3641.26    65.8 3639.17     119 3623.67   232.3 3581.75
   255.9 3575.76   265.2 3571.69     284 3569.79   293.6 3571.64   302.8 3573.36
   319.7 3569.58   337.2 3568.29   354.6 3572.06   366.2 3571.88   377.9 3569.32
   387.5  3570.7     411 3569.58   443.9 3571.39   462.1 3578.31   491.2 3598.13
   505.7 3605.06   523.1 3608.87   538.2 3617.61   553.8 3621.12     591 3620.67
     611 3633.09   623.1  3642.7   629.4 3645.72   751.5 3668.62   771.1 3670.92
#Mann= 6 ,-1,0
       0      .1       0   265.2    .045       0   293.6     .12       0
  507.42     .06       0  557.42     .08       0  667.42     .12       0
#XS Ineff= 2 , 0
                           304.4         3580.48
Permanent Ineff=
       F       F
Bank Sta=265.2,293.6
XS Rating Curve= 0 ,0
Exp/Cntr(USF)=0,0
Exp/Cntr=0.3,0.1

Type RM Length L Ch R = 1 ,593     ,225.5,223.7,222.8
BEGIN DESCRIPTION:
Area disconnected without IFA
END DESCRIPTION:
XS GIS Cut Line= 4
2287789.27975595595806.539414236 2287969.9200318595708.190819606
2288136.51050842595591.7781973912288293.06541415595224.476303162
#Sta/Elev= 30
       0 3665.82    59.2 3644.16   117.2 3606.46   153.6 3589.88   185.5 3572.19
   242.6 3556.99   249.7 3555.86   269.8 3557.03     287 3561.51   325.5 3560.48
   354.8 3561.83   369.5 3558.55     389 3559.11   418.3 3575.77   446.5 3579.31
   468.3 3575.77   472.6 3576.54   481.3 3581.24   507.4 3588.89   569.2 3602.57
   590.5 3613.69   620.5 3613.59   630.1 3611.84   642.3  3618.4   659.6 3624.22
   691.1 3631.73   711.8 3638.67   742.9 3645.27   779.5 3657.47   808.2 3663.38
#Mann= 7 ,-1,0
       0     .12       0      60      .1       0   242.6    .045       0
   269.8     .06       0  418.91     .12       0  528.91     .06       0
  638.91      .1       0
#XS Ineff= 1 ,-1
  355.23808.1868 3572.59
Permanent Ineff=
       F
Bank Sta=242.6,269.8
XS Rating Curve= 0 ,0
Exp/Cntr(USF)=0,0
Exp/Cntr=0.3,0.1

Type RM Length L Ch R = 1 ,369     ,201.8,199,199.5
XS GIS Cut Line= 4
2287879.59989387595943.0231782122288094.36111072595898.866666338
2288317.15078427595712.2050479592288437.57763483 595391.06677978
#Sta/Elev= 30
       0 3652.47    29.2 3645.81    61.8 3635.69    90.4  3620.6   135.3 3601.01
   143.5 3599.35   151.7 3594.82   159.9 3593.97   174.8 3586.72   224.6 3574.19
   235.9 3568.65   250.1 3554.38  260.013547.902   275.7  3545.8  290.433547.781
   318.3 3554.28   338.2 3554.44   360.9 3559.42   400.6 3558.75     471 3554.41
   513.1 3560.38   568.7 3572.36   592.3 3580.07   651.3 3593.64   662.7 3597.51
   679.7 3606.59   713.9 3603.47     731 3611.01   820.7 3629.32   852.9 3640.43
#Mann= 8 ,-1,0
       0      .1       0      70     .12       0  259.25     .06       0
  260.01    .045       0  290.43     .06       0  409.25     .12       0
   569.9     .06       0   759.9      .1       0
Bank Sta=260.01,290.43
XS Rating Curve= 0 ,0
Exp/Cntr(USF)=0,0
Exp/Cntr=0.3,0.1