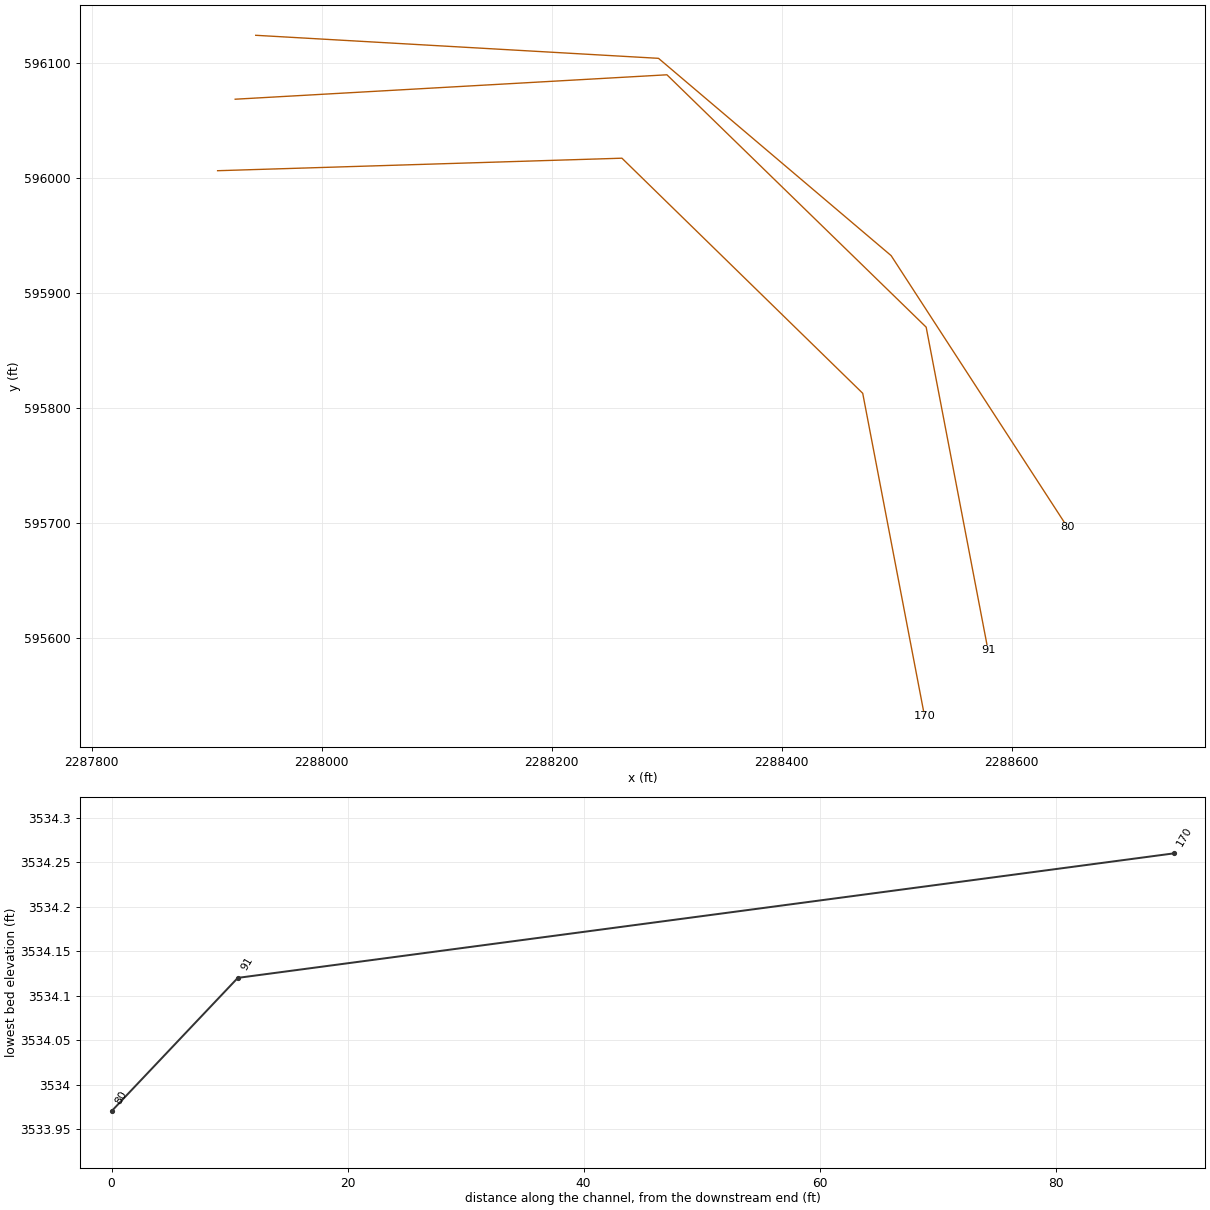
HEC-RAS study REDRN_2.prj: REDRN_2

--- REDRN_2.g01 (geometry) --- (continued)

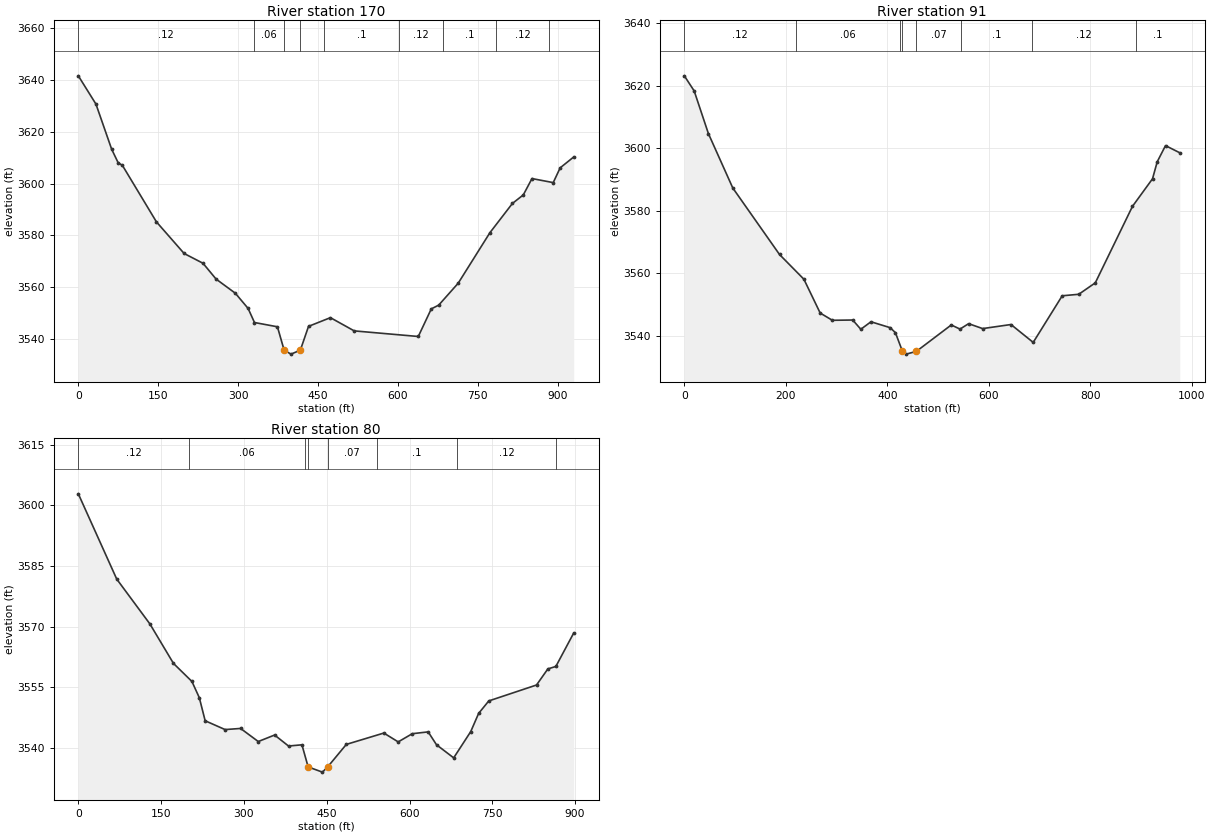
Type RM Length L Ch R = 1 ,170     ,79.4,79.3,79.6
XS GIS Cut Line= 4
2287909.55766012 596006.602213542288261.09909689596017.477512873
2288470.43795066595813.0802816852288524.23423898595532.144109326
#Sta/Elev= 30
       0 3641.56    33.1 3630.67    62.6 3613.27    74.9 3608.01    82.7 3607.06
   146.7 3585.25   198.7 3573.06   234.1  3569.3   258.7  3563.2   294.8 3557.75
   318.8 3551.89   330.8 3546.45   373.9  3544.8   386.5 3535.78   399.4 3534.26
  416.94 3535.79   432.3 3544.97   473.4 3548.32   518.1 3543.22   638.4 3541.06
   662.8  3551.7   676.8 3553.16   713.4 3561.62   772.9 3581.08   815.2 3592.37
   835.6 3595.65   851.9 3601.95   891.8 3600.39   904.8 3606.08   930.3 3610.28
#Mann= 9 ,-1,0
       0     .12       0     330     .06       0   386.5    .045       0
  416.94     .06       0  461.71      .1       0  601.71     .12       0
  684.29      .1       0  784.29     .12       0  884.29     .06       0
Bank Sta=386.5,416.94
XS Rating Curve= 0 ,0
Exp/Cntr(USF)=0,0
Exp/Cntr=0.3,0.1

Type RM Length L Ch R = 1 ,91      ,10.4,10.7,12.8
XS GIS Cut Line= 4
2287924.84624789596068.7624625352288300.20976891596089.995189804
2288525.60263598595870.579688109 2288579.3989243595589.643515749
#Sta/Elev= 30
       0 3623.13    19.4  3618.3    47.4 3604.67    95.5 3587.26   187.6 3565.99
   235.7 3558.07   267.8 3547.26   291.8 3544.94   331.9 3545.03   347.9 3542.07
   367.9 3544.47   405.8 3542.58   416.1 3540.98429.98053535.002   437.3 3534.12
   457.4    3535   526.2 3543.45   543.4 3542.13   560.4 3543.86     588 3542.29
   643.9 3543.59   687.7 3537.87   744.9 3552.78   777.5 3553.26   810.1 3556.92
   883.4 3581.39   922.9  3590.2   932.2 3595.65   948.5 3600.81   976.6 3598.52
#Mann= 8 ,-1,0
       0     .12       0     220     .06       0  425.96     .07       0
429.9805    .045       0   457.4     .07       0  545.96      .1       0
  685.96     .12       0  890.52      .1       0
Bank Sta=429.9805,457.4
XS Rating Curve= 0 ,0
Exp/Cntr(USF)=0,0
Exp/Cntr=0.3,0.1

Type RM Length L Ch R = 1 ,80      ,,,
XS GIS Cut Line= 4
2287942.70291742596124.3361930622288292.88483016596104.306017744
2288495.14659094595932.7735646542288648.46078276595696.664638321
#Sta/Elev= 30
       0 3602.84    69.6 3581.74   129.7 3570.64   172.4 3560.87   205.8 3556.41
   219.2 3552.39   229.8 3546.68   265.9  3544.5     294 3544.78     326 3541.54
   355.6 3543.15   380.8 3540.43   405.1 3540.73  416.36 3535.26   442.2 3533.97
   451.8 3535.27   485.5 3540.83   553.5 3543.64   579.5 3541.45     605 3543.48
   633.8 3543.93   648.9 3540.74     680  3537.5   710.9    3544   725.2  3548.5
   743.6 3551.59   830.1 3555.53   850.6 3559.51   865.1 3560.12   897.5 3568.41
#Mann= 8 ,-1,0
       0     .12       0     200     .06       0  410.75     .07       0
  416.36    .045       0   451.8     .07       0  540.75      .1       0
  685.96     .12       0  865.96      .1       0
Bank Sta=416.36,451.8
XS Rating Curve= 0 ,0
Exp/Cntr(USF)=0,0
Exp/Cntr=0.3,0.1
LCMann Table=0

Chan Stop Cuts=-1
Use User Specified Reach Order=0
Composite Channel Slope=5